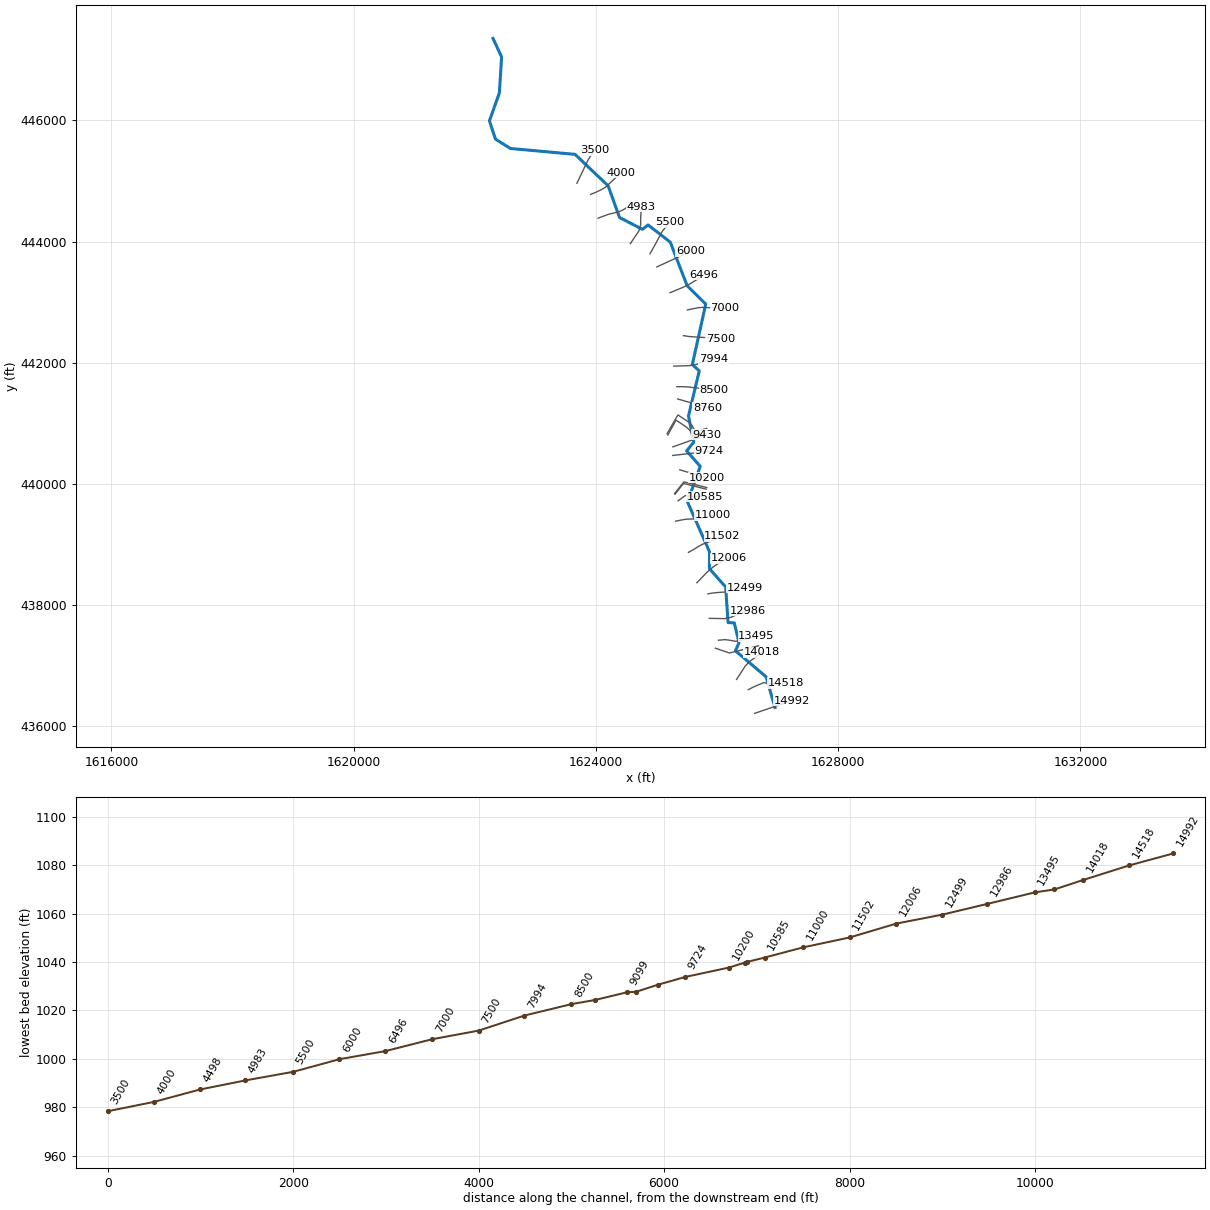
--- WHTSTNECK.prj (project) ---

Proj Title=WHTSTNECK
Current Plan=p01
Default Exp/Contr=0,0
English Units
Geom File=g01
Flow File=f01
Plan File=p01
BEGIN DESCRIPTION:
---------- MODELED AS PART OF WVEMD CTP PROGRAM, 2023----------
Stream Name: Whetstone Creek
Flood Zone:  AFH
Wetzel County, WV
HEC-RAS Version: RAS 6.3
Vertical Datum: NAVD88
Projection: NAD 1983 StatePlane West Virginia S FIPS 4702 (US Feet)
Terrain: 1-meter West Virginia FEMA R3 South Central (collected 2018-2020)
Land Use: 2019 NLCD
Hydrologic Method:
WV 2010 Regional Regression Equations
Additional Model Notes:
None
END DESCRIPTION:
DSS Export Rating Curves= 0
DSS Export Rating Curve Sorted= 0
DSS Export Volume Flow Curves= 0
DXF OffsetX= 0
DXF OffsetY= 0
DXF ScaleX= 0
DXF ScaleY= 0

--- WHTSTNECK.p01 (plan) ---

Plan Title=Floodplain
Program Version=4.00
Geom File=g01
Flow File=f01
K Sum by GR=0
Std Step Tol=0.01
Critical Tol=0.01
Num of Std Step Trials=20
Max Error Tol=0.3
Flow Tol Ratio=0.001
Split Flow NTrial=30
Split Flow Tol=0.02
Split Flow Ratio=0.02
Log Output Level=0
Friction Slope Method=1
Unsteady Friction Slope Method=2
Unsteady Bridges Friction Slope Method=1
Global Log Level=0
CheckData=False
Run HTab=0
Run UNet=0
Run PostProcess=0
UNET Theta=0
UNET Theta Warmup=0
UNET ZTol=0
UNET ZSATol=0
UNET MxIter=0
UNET MaxInSteps=0
UNET DtIC=0
UNET DtMin=0
UNET MaxCRTS=0
UNET WFStab=0
UNET SFStab=0
UNET WFX=0
UNET SFX=0
UNET DSS MLevel=0
UNET DZMax Abort=0
UNET Convert EG Bridges=0
UNET Use Existing IB Tables=0
UNET Froude Limit=0
UNET Froude Power=0
Write IC File=0
Echo Input=False
Echo Output=False
Write Detailed=0

--- WHTSTNECK.f01 (steady flow) ---

Flow Title=Flow
Program Version=6.31
Number of Profiles= 1
Profile Names=F01pct
River Rch & RM=WHTSTNECK,Main,14992
     705
River Rch & RM=WHTSTNECK,Main,12986
     784
River Rch & RM=WHTSTNECK,Main,10399
     899
River Rch & RM=WHTSTNECK,Main,10200
    1010
River Rch & RM=WHTSTNECK,Main,7500
    1180
River Rch & RM=WHTSTNECK,Main,4498
    1360
River Rch & RM=WHTSTNECK,Main,1932
    1640
Boundary for River Rch & Prof#=WHTSTNECK,Main            , 1
Up Type= 0
Dn Type= 3
Dn Slope=0.005
DSS Import GetInterval= 0
DSS Import GetPeak= 0
DSS Import FillOption= 0

--- WHTSTNECK.g01 (geometry) ---

Geom Title=Geometry
Program Version=6.31

River Reach=WHTSTNECK       ,Main
Reach XY= 30
1626957.65609864436300.9894648481626811.38114061436807.306731372
 1626304.8184634437238.179087112     1626364.438      437372.464
     1626285.586      437698.786     1626183.148      437704.066
      1626143.37       438292.29      1625874.78      438595.379
     1625877.596      438872.418     1625512.552      439699.311
     1625723.763      440284.718     1625499.175      440540.636
     1625617.806      440686.724     1625529.449      441115.131
     1625707.218      441862.468     1625593.164      441966.665
     1625814.584      442966.399     1625507.624      443268.784
     1625228.825      443990.071      1624862.02       444274.15
     1624769.792       444200.93     1624390.667      444397.357
     1624203.041      444920.458     1623656.355      445440.038
     1622588.329      445537.195     1622341.916      445693.139
     1622242.646      445993.764     1622406.687      446454.909
     1622443.649      447049.469     1622301.082      447357.133

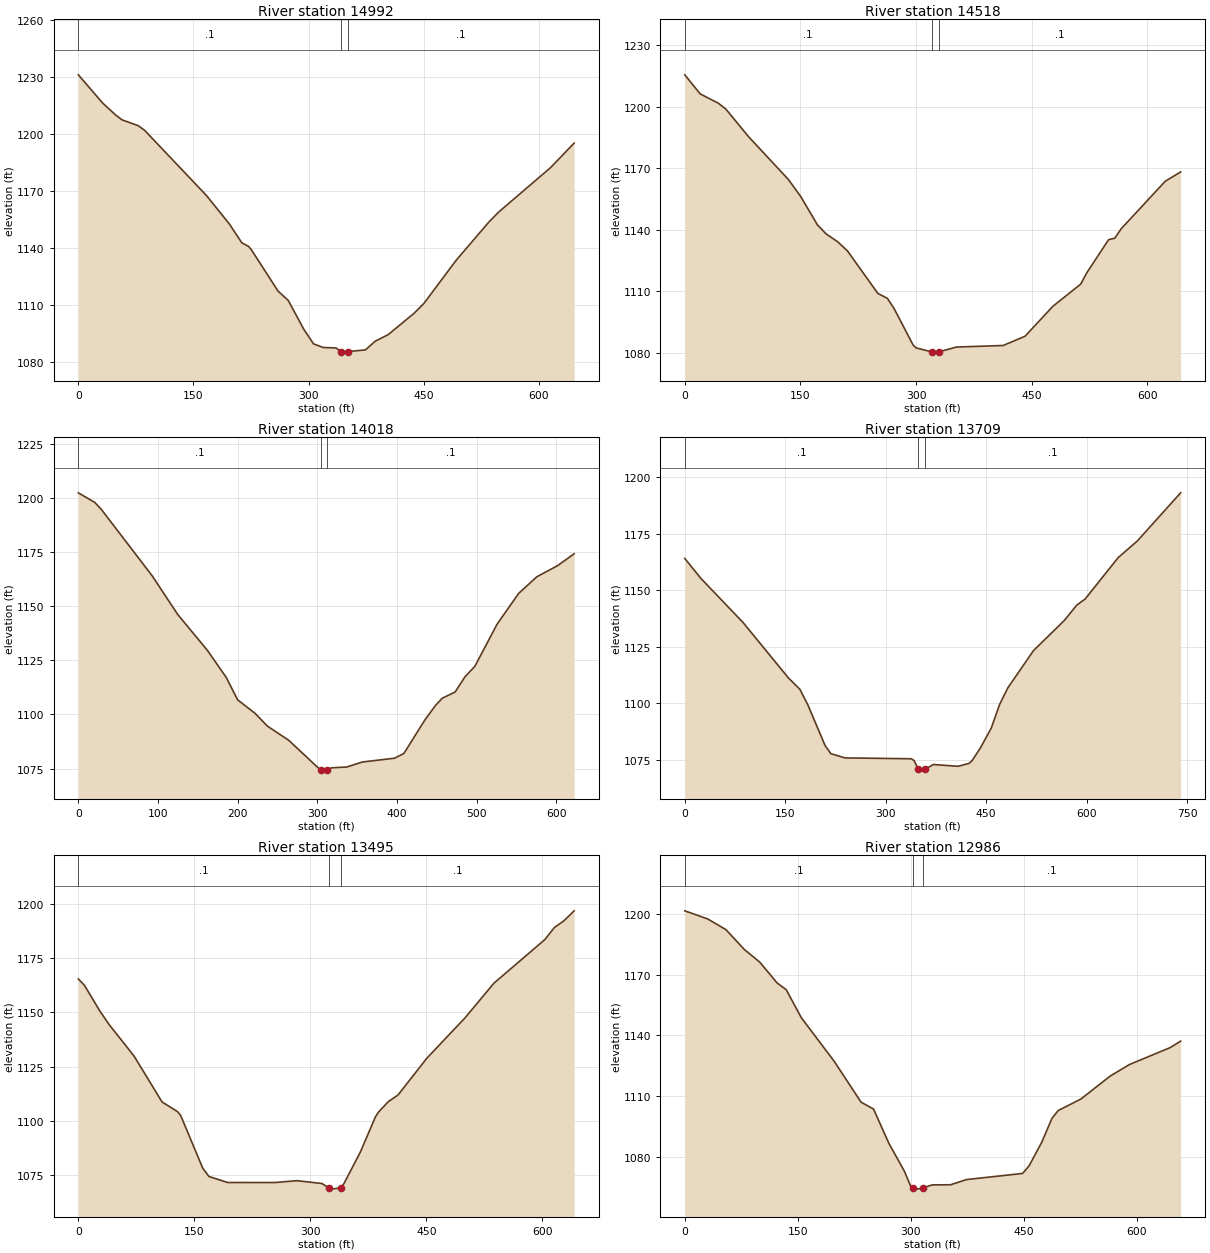
Type RM Length L Ch R = 1 ,14992   ,473.2,474,468.1
XS GIS Cut Line= 2
1626622.22944986 436203.602916721627233.33821856436413.671555961
#Sta/Elev= 30
       0 1231.28    31.6 1216.48    48.5 1210.19      57 1207.57    78.1 1204.52
    86.6 1201.99     167 1167.75   196.6 1152.92   213.1 1142.87   221.9 1140.97
   225.7 1139.12   260.3 1117.45   273.6 1112.54   293.8  1097.4   306.5 1089.71
   319.2 1087.76   335.9 1087.55   342.2 1085.51   344.6 1084.81   351.6 1085.65
   374.2 1086.51   386.9 1091.08   403.8 1094.53   437.7 1105.82   450.3 1110.92
   492.6 1133.77   534.9 1153.72   547.6 1158.98   615.3 1182.39646.2064 1195.36
#Mann= 3 ,-1,0
       0      .1       0   342.2    .045       0   351.6      .1       0
Bank Sta=342.2,351.6
XS Rating Curve= 0 ,0
Exp/Cntr(USF)=0,0
Exp/Cntr=0.3,0.1

Type RM Length L Ch R = 1 ,14518   ,494.9,500.2,503.7
XS GIS Cut Line= 6
 1626517.4420431436595.3183802521626608.62525967436643.032523677
1626770.63805901436710.7216927561626945.15444225436688.767012253
1627034.72119226436686.9212154151627131.71640509436706.552737832
#Sta/Elev= 30
       0 1215.46    19.9 1206.19    43.6 1201.61    53.3 1198.75    82.9 1185.24
   134.2 1164.54   150.2 1156.27   171.9 1142.46   182.9 1138.09   198.2 1134.16
     211 1129.67   250.3    1109   262.8 1106.56   271.5 1101.56   296.1 1083.83
   300.1 1082.43  320.11 1080.51   324.2 1079.89   329.4 1080.51   352.3 1082.85
   412.9 1083.61   441.3 1088.13   477.4 1102.72   513.4  1113.5   521.4 1119.06
   549.6 1135.15   557.7 1135.89   565.9 1140.45     623 1163.59643.0206 1168.15
#Mann= 3 ,-1,0
       0      .1       0  320.11    .045       0   329.4      .1       0
Bank Sta=320.11,329.4
XS Rating Curve= 0 ,0
Exp/Cntr(USF)=0,0
Exp/Cntr=0.3,0.1

Type RM Length L Ch R = 1 ,14018   ,309.4,309.3,303.5
XS GIS Cut Line= 6
1626323.65634142436764.5411389171626462.78303167436979.733950004
1626531.00730467437055.1911481771626594.40383142437101.296370924
1626667.32363309437154.4481675031626743.19060734 437213.32567443
#Sta/Elev= 30
       0 1202.39    20.6 1197.98    28.6 1194.87    92.9 1163.97   124.7 1146.25
   162.3 1129.53   185.8 1117.07     200 1106.79   221.9 1100.53   237.5  1094.6
   264.2 1088.09  304.49 1074.21   308.7 1073.83  312.37 1074.21   317.9 1075.36
   337.1 1075.73   356.9 1078.06     397 1079.79   408.8 1081.97   435.1 1097.43
   448.5 1104.17   457.1 1107.54   473.1 1110.35   485.7 1117.49   497.9 1122.23
   525.8 1141.68   552.9 1155.91   575.7 1163.59   601.8 1168.75622.6343 1174.24
#Mann= 3 ,-1,0
       0      .1       0  304.49    .045       0  312.37      .1       0
Bank Sta=304.49,312.37
XS Rating Curve= 0 ,0
Exp/Cntr(USF)=0,0
Exp/Cntr=0.3,0.1

Type RM Length L Ch R = 1 ,13709   ,208.3,213.6,212.2
XS GIS Cut Line= 3
1625973.99957793437281.0448703611626204.91281774437201.161371185
1626686.71017214437319.738440275
#Sta/Elev= 30
       0 1164.01    24.1 1155.18    86.9 1135.72   154.6 1111.22   171.9 1106.12
   183.8 1099.24   209.5 1081.29   218.1 1077.66   239.3 1075.79   338.3 1075.41
   342.4 1074.64   348.9 1070.74   354.7 1069.94   358.9 1070.72   358.9 1070.73
   371.2 1072.86   408.3 1072.08   424.8 1073.38   428.9 1074.53   441.5 1080.21
   457.7 1088.98   470.1  1099.4   482.4 1106.75   520.8 1123.27   566.5 1136.49
   585.4 1143.38   597.8 1146.05   647.2 1164.38   675.8 1171.74   740.5 1193.05
#Mann= 3 ,-1,0
       0      .1       0   348.9    .045       0   358.9      .1       0
Bank Sta=348.9,358.9
XS Rating Curve= 0 ,0
Exp/Cntr(USF)=0,0
Exp/Cntr=0.3,0.1

Type RM Length L Ch R = 1 ,13495   ,503.6,509.1,505.6
XS GIS Cut Line= 6
1626024.32590334437411.923702419 1626131.8640741437422.642513007
1626227.04531418437409.5788908451626305.56976342437394.062189594
1626403.96031468437412.0450932531626653.01296617437475.707039416
#Sta/Elev= 30
       0 1165.33     7.8  1162.5    27.9 1150.58      40 1144.31    72.1 1129.89
   108.3 1108.78   128.5  1104.3   132.5 1102.49   160.8 1078.42   168.9 1074.52
   193.1 1071.75   254.2 1071.73   282.7 1072.59   315.2 1071.28  323.56 1069.31
   327.4  1068.7   339.6 1069.32   343.7 1071.36   364.7 1085.71   384.4 1102.03
   388.5 1104.22     401 1108.96   413.4 1111.96   450.7 1128.88   500.3 1147.53
   537.4 1163.37   603.3 1183.45   615.7 1188.99   628.1 1192.12641.2843 1196.69
#Mann= 3 ,-1,0
       0      .1       0  323.56    .045       0   339.6      .1       0
Bank Sta=323.56,339.6
XS Rating Curve= 0 ,0
Exp/Cntr(USF)=0,0
Exp/Cntr=0.3,0.1

Type RM Length L Ch R = 1 ,12986   ,484,487.2,483.6
XS GIS Cut Line= 6
1625873.45612635437773.7120208441626129.65705751437768.688408837
1626231.66932067437791.7362630071626316.14224884437828.919587582
1626410.79527476437866.1042245031626507.69304684437903.036565334
#Sta/Elev= 30
       0 1201.53    30.7 1197.47    54.7 1192.21      79 1182.45    99.5 1176.19
   122.7 1165.85   134.7 1162.56   154.7 1148.73   198.7 1127.02   234.1 1106.95
   250.7 1103.55   271.1 1086.57   291.6 1072.86   299.8 1065.61  302.79 1064.58
     308 1063.97   316.2 1064.56   328.5 1066.06   353.1 1066.14   374.4 1068.71
   448.7 1071.72   457.4 1075.57     474  1087.1   487.5 1098.84   495.8 1102.78
   526.2 1108.54   564.8  1119.8   590.5 1125.55   644.5 1133.89658.5208 1137.11
#Mann= 3 ,-1,0
       0      .1       0  302.79    .045       0   316.2      .1       0
Bank Sta=302.79,316.2
XS Rating Curve= 0 ,0
Exp/Cntr(USF)=0,0
Exp/Cntr=0.3,0.1

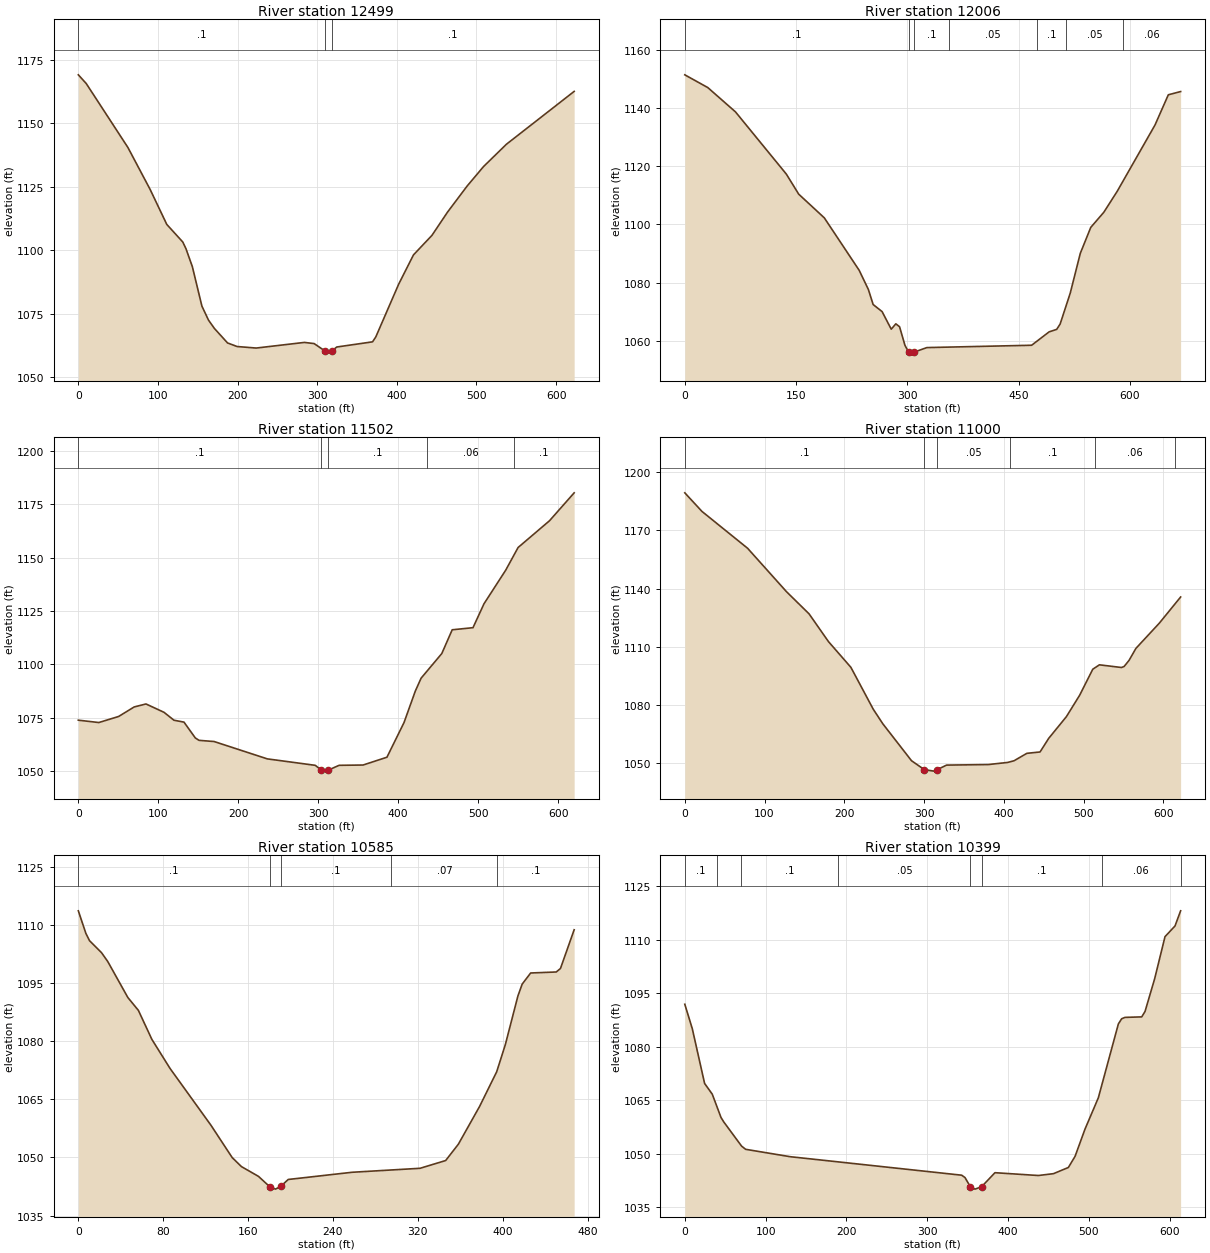
Type RM Length L Ch R = 1 ,12499   ,488.6,493.2,493.9
XS GIS Cut Line= 6
1625850.32198626 438178.999268011625946.82638642  438194.4500245
1626037.57358025438202.5123443451626114.93989535438207.209841505
1626213.12014517 438226.729159431626463.12095751438282.976094171
#Sta/Elev= 30
       0 1169.17     9.9 1165.75    62.3 1140.53    90.2    1124   111.1 1110.23
   131.2  1103.3   135.2 1100.65   143.2  1093.6   155.2 1078.05   163.5 1072.52
   170.9 1069.25   187.4 1063.54   199.4 1062.13   223.4 1061.53   283.9 1063.75
   296.1 1063.29   309.3 1060.49   312.7 1059.53  318.71 1060.48   324.6 1061.94
   369.5 1063.98   373.6 1065.92   402.3 1086.68   420.9 1098.23   444.1 1105.92
   463.8 1115.14   488.4 1125.39   508.9 1133.03   537.6 1141.81622.6987 1162.64
#Mann= 3 ,-1,0
       0      .1       0   309.3    .045       0  318.71      .1       0
Bank Sta=309.3,318.71
XS Rating Curve= 0 ,0
Exp/Cntr(USF)=0,0
Exp/Cntr=0.3,0.1

Type RM Length L Ch R = 1 ,12006   ,499.8,503.5,500.6
XS GIS Cut Line= 6
1625668.58416076438362.2830221651625846.91516893438546.275108263
1625926.51507534 438614.197544591626002.67994925 438668.02420859
1626096.16663893438718.4456956681626193.09492275438765.668370262
#Sta/Elev= 30
       0 1151.32      31 1146.95    68.3 1138.61   136.8 1117.28   153.5 1110.39
     188 1102.26     235 1084.27   247.4 1077.68   253.8 1072.54   265.9  1070.1
   278.2 1064.07   284.4 1065.91   289.4 1064.91   296.7 1058.54  301.63  1056.2
   305.1 1055.86     309  1056.2   326.2 1057.76   467.4 1058.56     491 1063.16
   501.2 1064.01   505.8 1065.84   519.4 1076.42     533  1090.1   547.1 1098.99
   564.7 1104.18   582.8  1111.4   633.7 1134.13   651.6 1144.47668.1747 1145.58
#Mann= 7 ,-1,0
       0      .1       0  301.63    .045       0     309      .1       0
  356.23     .05       0  474.14      .1       0  514.14     .05       0
  590.36     .06       0
Bank Sta=301.63,309
XS Rating Curve= 0 ,0
Exp/Cntr(USF)=0,0
Exp/Cntr=0.3,0.1

Type RM Length L Ch R = 1 ,11502   ,501.3,502.2,496.9
XS GIS Cut Line= 6
1625529.46764109438864.1064935921625613.44778809438910.692686498
1625688.98044543 438957.573170171625754.50721726438994.972045511
1625919.36089018439056.4013845921626088.43273051439128.197172761
#Sta/Elev= 30
       0 1073.95    25.6 1072.84    50.4 1075.68    69.9 1080.14    84.6 1081.53
   107.1 1077.63   119.6 1073.92   132.1 1073.04   146.3 1065.63     151 1064.51
   169.8 1063.96   236.3 1055.85   296.3 1052.83   303.9 1050.59   309.1 1050.12
   312.6  1050.6   326.1 1052.84     356 1052.97   385.9 1056.62   407.2 1072.78
   421.4 1087.57   428.6 1093.58   454.5 1105.11   467.5 1116.21   493.5  1117.2
   507.3  1128.4   534.4 1144.08   549.9 1154.69   589.2 1167.21 619.998 1180.26
#Mann= 5 ,-1,0
       0      .1       0   303.9    .045       0   312.6      .1       0
  436.31     .06       0  545.09      .1       0
Bank Sta=303.9,312.6
XS Rating Curve= 0 ,0
Exp/Cntr(USF)=0,0
Exp/Cntr=0.3,0.1

Type RM Length L Ch R = 1 ,11000   ,412.8,414.8,414.5
XS GIS Cut Line= 6
1625319.13833734 439378.89811492 1625411.8438606439398.871500179
1625499.13633692 439412.404937671625674.09956968439417.781895429
1625748.94489242 439428.398344011625929.81657793439478.881838843
#Sta/Elev= 30
       0 1189.26    21.5  1179.7    78.7 1160.74   127.5 1138.38   155.8 1126.97
   180.1  1112.7   208.2 1099.47   236.2 1077.94   248.2 1070.43   284.2  1051.4
   300.2 1046.82   312.2 1046.03  316.52 1046.81   328.2 1049.13   380.5 1049.41
   404.9 1050.51   412.8 1051.37   428.9 1055.19   445.4 1055.89   456.2 1062.88
   478.4 1074.06     495 1085.06   511.5 1098.48   519.8 1100.74   547.5 1099.36
   550.8 1099.91   556.9 1102.99   565.6 1109.21   594.8 1122.13621.6205 1135.64
#Mann= 6 ,-1,0
       0      .1       0   300.2    .045       0  316.52     .05       0
  408.22      .1       0  513.81     .06       0  614.35      .1       0
Bank Sta=300.2,316.52
XS Rating Curve= 0 ,0
Exp/Cntr(USF)=0,0
Exp/Cntr=0.3,0.1

Type RM Length L Ch R = 1 ,10585   ,187,186.2,185.7
XS GIS Cut Line= 3
1625358.40902456439715.5899844561625475.42720831439801.280465466
1625796.99686285439780.088195969
#Sta/Elev= 30
       0 1113.67     7.1 1107.85    10.5 1105.98    21.9 1102.85    27.7  1100.6
    46.7 1091.28    56.6 1087.97    69.3 1080.49    86.4 1072.99     125 1058.31
     145 1049.97   153.7 1047.64   169.8 1045.11   180.2 1042.49   185.8 1041.82
  190.63  1042.5   197.8 1044.31     258 1046.17   322.1  1047.2   346.2  1049.2
   358.2 1053.43   378.2 1063.18   394.3 1072.12   402.5 1079.18   414.3 1091.69
   418.3 1094.74   426.3 1097.62   450.4 1097.88   454.4 1098.78467.3055 1108.78
#Mann= 5 ,-1,0
       0      .1       0   180.2    .045       0  190.63      .1       0
  295.04     .07       0  395.04      .1       0
Bank Sta=180.2,190.63
XS Rating Curve= 0 ,0
Exp/Cntr(USF)=0,0
Exp/Cntr=0.3,0.1

Type RM Length L Ch R = 1 ,10399   ,28.9,28.4,29
XS GIS Cut Line= 3
1625307.73185838439825.2369440281625446.86371464  440003.0677272
1625822.79614746439908.163215973
#Sta/Elev= 30
       0 1091.94     9.3 1085.06    24.5 1069.72      34  1066.7    44.8 1060.17
    48.2 1058.92    70.2 1052.15    75.3 1051.23   130.4 1049.16   342.6 1043.97
   346.7 1043.31  353.33 1040.73   359.1 1040.06   367.2 1040.72   383.8 1044.67
   437.5 1043.88   456.2  1044.4   474.6 1046.13   482.9 1049.25   495.2  1056.9
   511.7 1065.68   536.5 1086.42   540.6 1087.87   544.7 1088.25   565.4 1088.39
   569.5 1089.92   581.4  1099.1   594.2  1110.9   606.6 1113.91613.5175 1118.15
#Mann= 8 ,-1,0
       0      .1       0      40     .05       0      70      .1       0
     190     .05       0  353.33    .045       0   367.2      .1       0
  515.79     .06       0  613.52      .1       0
Bank Sta=353.33,367.2
XS Rating Curve= 0 ,0
Exp/Cntr(USF)=0,0
Exp/Cntr=0.3,0.1

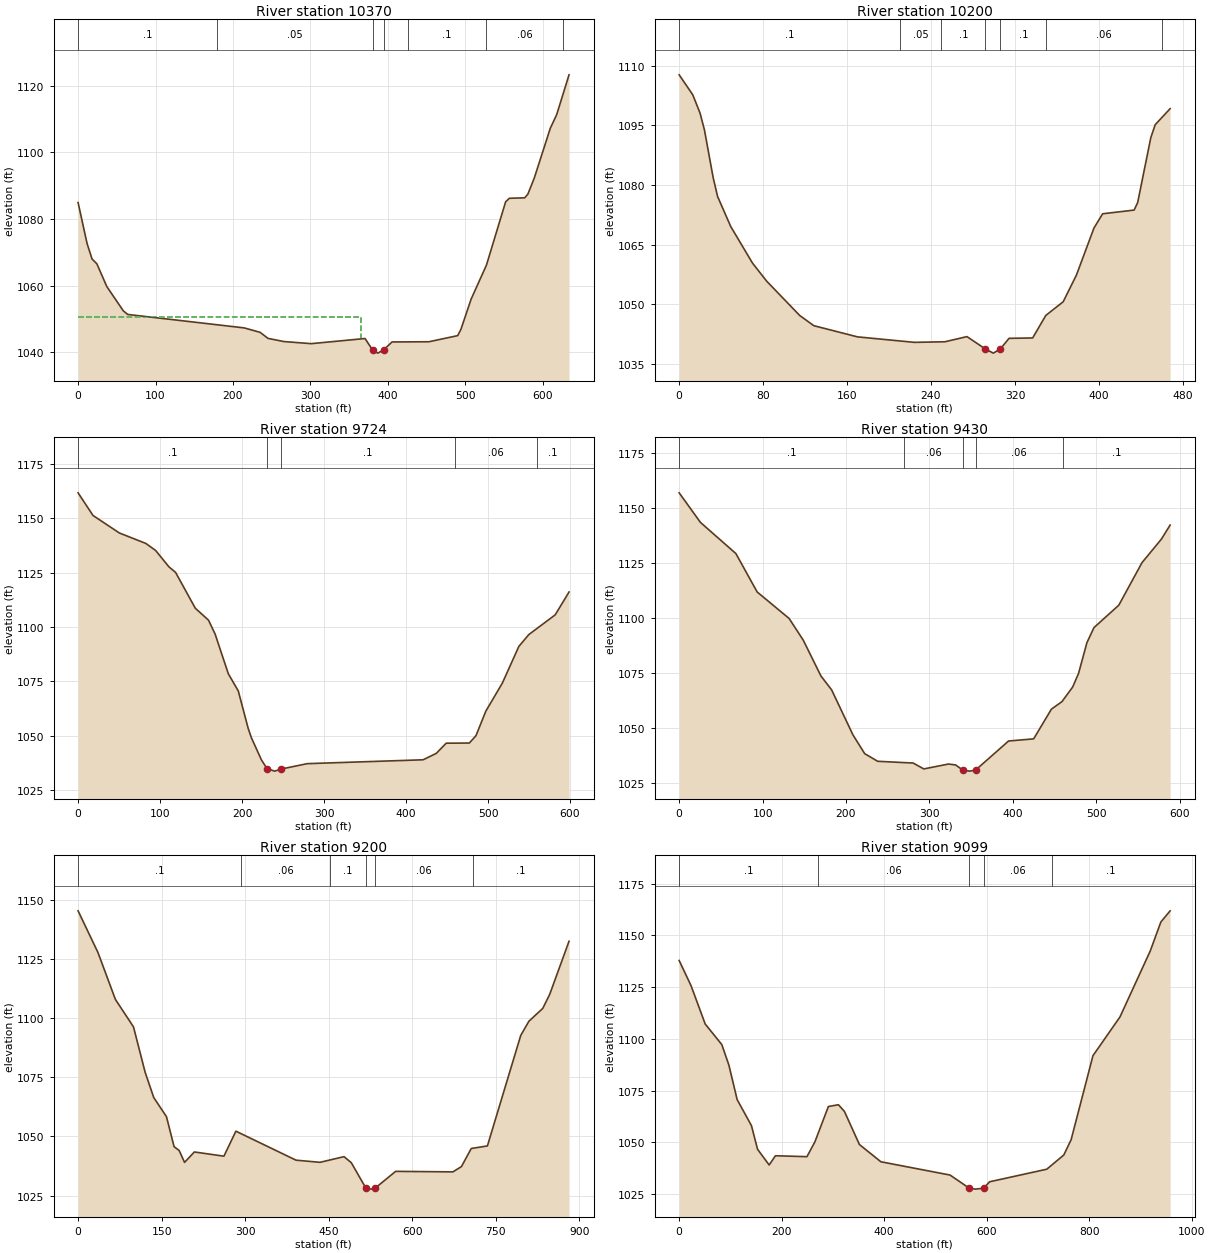
Type RM Length L Ch R = 1 ,10370   ,170.9,170.1,170.2
XS GIS Cut Line= 3
1625300.82133571 439837.675884821625455.61704334440029.327713316
1625831.54947616439934.423202089
#Sta/Elev= 30
       0  1084.9    11.6 1072.62      18 1067.99    24.3 1066.52    37.1 1059.71
    58.4 1052.43    64.1 1051.34   214.5 1047.31   235.1 1045.98   245.3 1044.16
   265.9 1043.21   301.1 1042.58   370.6 1044.12   380.3 1040.71   387.1 1039.74
  394.55 1040.71   405.5 1043.09   453.1 1043.15   490.3 1044.99   494.5 1046.89
   507.6 1055.92   527.4 1066.12   552.2 1085.12     557 1086.18   576.9 1086.32
     581 1087.46   589.3 1092.32   609.9 1107.18   618.2 1111.31634.0845 1123.21
#Mann= 7 ,-1,0
       0      .1       0     180     .05       0   380.3    .045       0
  394.55     .05       0  426.36      .1       0  526.36     .06       0
  626.36      .1       0
#XS Ineff= 2 , 0
          365.85 1050.71
Permanent Ineff=
       F       F
Bank Sta=380.3,394.55
XS Rating Curve= 0 ,0
Exp/Cntr(USF)=0,0
Exp/Cntr=0.3,0.1

Type RM Length L Ch R = 1 ,10200   ,476.1,476.1,479.2
XS GIS Cut Line= 2
1625385.04755691440228.1934070321625833.74175811440095.481037664
#Sta/Elev= 30
       0 1107.74    12.9 1102.74    19.9 1098.11    24.1 1093.85    32.4 1081.85
    36.6 1077.14    49.1 1069.58    69.9 1060.35    83.4 1055.81   114.9 1047.17
   128.3 1044.61     170 1041.79   224.3 1040.41   253.3 1040.56   274.3 1041.86
   291.9 1038.73   299.4  1037.7  305.97 1038.72   314.4 1041.42   336.9 1041.52
   349.4 1047.18     366 1050.63   378.6 1057.33   395.3 1069.17   403.6 1072.77
   433.6  1073.7     437 1075.61   449.5 1091.93   453.7 1095.19467.9092 1099.22
#Mann= 7 ,-1,0
       0      .1       0     210     .05       0     250      .1       0
   291.9    .045       0  305.97      .1       0     350     .06       0
     460      .1       0
Bank Sta=291.9,305.97
XS Rating Curve= 0 ,0
Exp/Cntr(USF)=0,0
Exp/Cntr=0.3,0.1

Type RM Length L Ch R = 1 ,9724    ,287.3,294,289.6
XS GIS Cut Line= 2
 1625269.9967698440465.1958442961625864.96241471440533.152293248
#Sta/Elev= 30
       0 1161.68    18.2 1151.28    50.4 1143.22    82.7 1138.41    94.7 1135.14
   110.8 1127.67   118.9 1125.12     143 1108.63   159.1 1103.15   167.2  1096.7
   183.3 1078.49   195.4 1070.62   207.5 1053.38   211.5 1049.02   223.6 1038.97
   230.4 1034.96   239.7 1033.78   247.81034.748   279.5 1037.21   420.8 1038.99
   436.9 1041.94     449 1046.62   477.2 1046.69   485.3 1050.06   497.3 1061.33
   517.5 1074.25   537.6 1091.09   549.7 1096.52   581.9 1105.59   598.8  1116.1
#Mann= 5 ,-1,0
       0      .1       0   230.4    .045       0   247.8      .1       0
     460     .06       0     560      .1       0
Bank Sta=230.4,247.8
XS Rating Curve= 0 ,0
Exp/Cntr(USF)=0,0
Exp/Cntr=0.3,0.1

Type RM Length L Ch R = 1 ,9430    ,237.3,230.2,220.9
XS GIS Cut Line= 2
1625272.10360063440606.6554018521625826.05109723440805.678454521
#Sta/Elev= 30
       0 1156.74    25.5 1143.33      68  1129.2    93.5 1111.79   131.8 1099.78
   148.8 1089.92     170 1073.68   182.8 1067.39   208.3 1047.03   222.4 1038.49
     238 1035.02   280.5 1034.23   293.3 1031.56     323 1033.78   331.5 1033.35
     340 1031.03   348.5 1030.56  355.42 1031.05   394.9 1044.21     425 1045.19
   446.3 1058.66     459 1062.09   471.8 1068.71   478.8 1074.83   488.8 1088.75
   497.3 1095.63   527.1  1105.8   554.9 1125.09   578.1 1135.72588.6154 1142.12
#Mann= 5 ,-1,0
       0      .1       0     270     .06       0     340    .045       0
  355.42     .06       0     460      .1       0
Bank Sta=340,355.42
XS Rating Curve= 0 ,0
Exp/Cntr(USF)=0,0
Exp/Cntr=0.3,0.1

Type RM Length L Ch R = 1 ,9200    ,106.4,101,99.6
XS GIS Cut Line= 6
1625187.98860503440801.2454822061625323.35522179441049.228023826
1625496.26048017440933.1994951781625554.27474449440878.597834638
1625611.15147422 440775.082186531625797.70714773440825.133708692
#Sta/Elev= 30
       0 1145.47    35.7 1127.83      67 1107.99    99.5 1096.37   120.4 1077.18
   135.9 1066.46   158.7  1058.4   172.4 1045.68   181.5 1044.08   191.2 1039.03
   208.8 1043.44   261.9 1041.66   283.4 1052.24   391.4 1039.97   434.5 1039.06
   477.6 1041.46   490.6 1038.93   516.6 1028.25   526.7 1027.72  534.12 1028.25
   570.3 1035.24   673.2 1035.02   688.5 1037.26   706.1 1044.91   735.1    1046
     795 1092.77   809.6 1098.75   834.5 1104.18   846.9 1110.08881.6846 1132.59
#Mann= 6 ,-1,0
       0      .1       0  292.52     .06       0  452.52      .1       0
   516.6    .045       0  534.12     .06       0  708.53      .1       0
Bank Sta=516.6,534.12
XS Rating Curve= 0 ,0
Exp/Cntr(USF)=0,0
Exp/Cntr=0.3,0.1

Type RM Length L Ch R = 1 ,9099    ,325.3,338.9,341.9
XS GIS Cut Line= 6
1625175.47572449440824.5649413951625355.20619044441135.111885717
1625528.11144882441019.0833570691625586.12571314440964.481696529
1625643.00244287440860.9660484221625829.55811638440911.017570583
#Sta/Elev= 30
       0 1137.88    23.1 1125.76    50.8 1107.22    83.2 1097.28      97 1087.39
   113.1 1070.73     141 1058.16     153  1046.7   175.6 1039.15   187.8  1043.6
   249.3 1043.15   264.8 1050.28   291.1 1067.36   310.7 1068.24   322.5 1064.99
   351.7 1049.02   393.6 1040.69   528.5 1034.28     566 1027.95     578 1027.48
   594.5 1027.95   605.5 1031.01   717.3  1037.1   750.5 1043.96   764.8 1051.34
   807.4 1091.92   860.1 1110.63   919.2 1142.49   939.9 1156.48957.9681 1161.88
#Mann= 5 ,-1,0
       0      .1       0     270     .06       0     566    .045       0
   594.5     .06       0   726.7      .1       0
Bank Sta=566,594.5
XS Rating Curve= 0 ,0
Exp/Cntr(USF)=0,0
Exp/Cntr=0.3,0.1

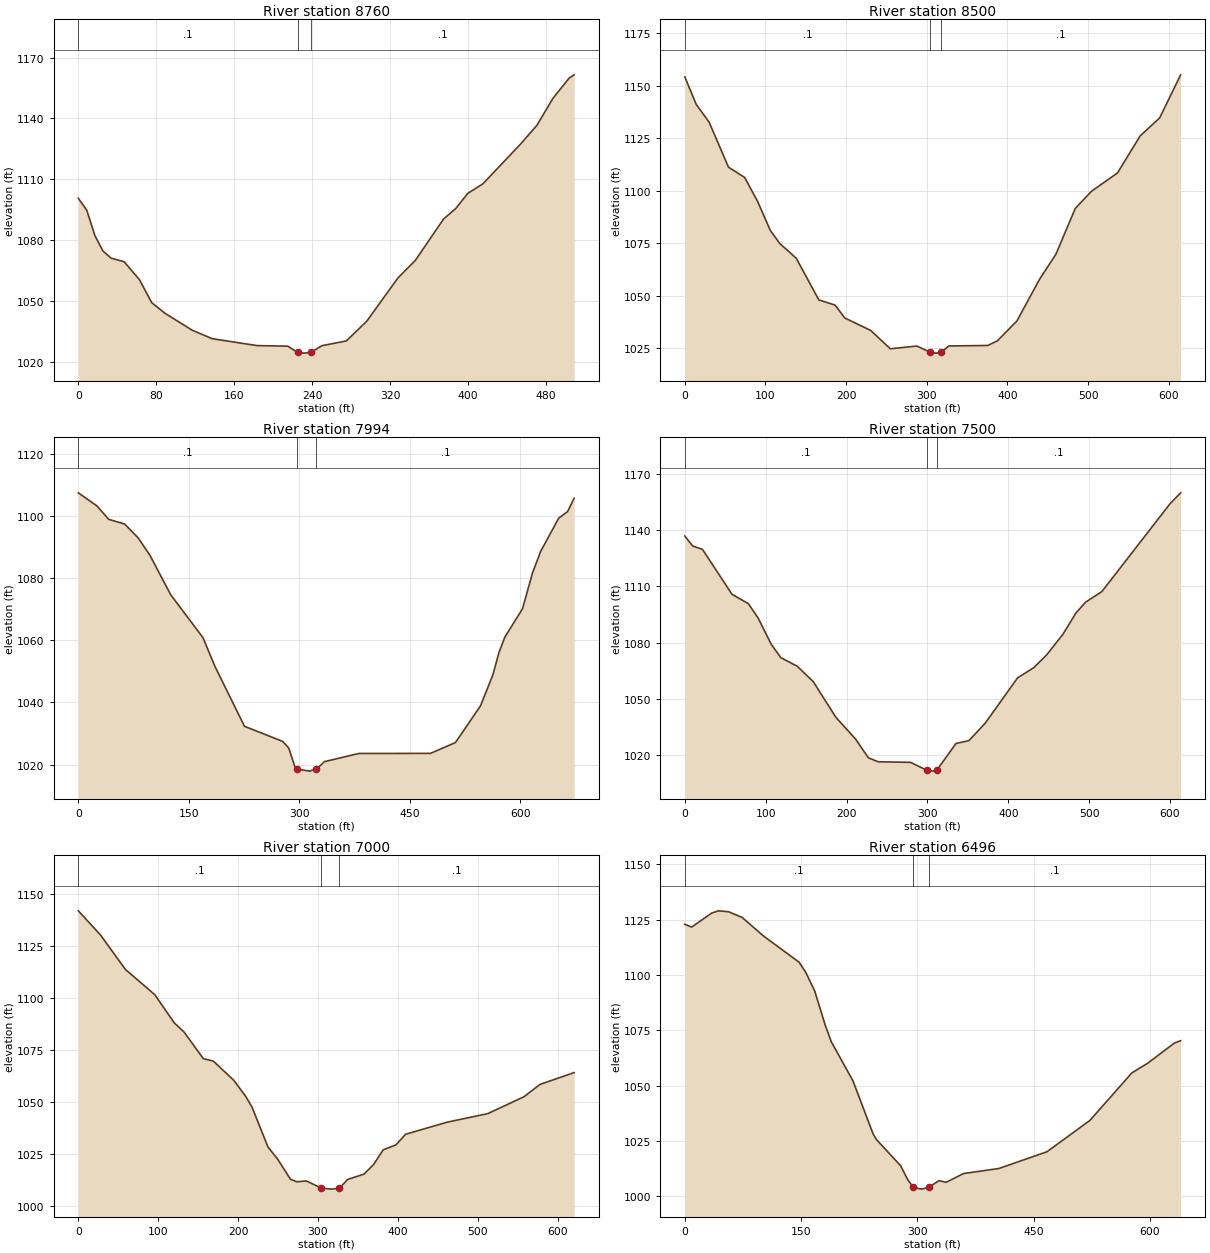
Type RM Length L Ch R = 1 ,8760    ,259.4,260.1,261.6
XS GIS Cut Line= 2
1625351.79358665441398.4511443641625840.93346233441257.396854635
#Sta/Elev= 30
       0 1100.64     8.7 1094.72      17 1082.27    25.3 1074.66    33.6 1071.14
      47  1069.4    62.8 1060.52    75.3 1049.24      89 1043.98   116.9 1035.65
   137.5 1031.46   183.5 1028.06   215.1 1027.78   225.1 1024.73   231.7 1024.35
  238.88 1024.74   250.1 1028.02   275.1 1030.35   295.9 1039.95   328.2 1061.42
   345.9 1069.98     375 1090.42   387.5  1095.6     400 1103.11   415.4 1107.78
     454 1127.34   470.8 1136.57   487.4 1149.97   504.1 1159.95509.0718 1161.47
#Mann= 3 ,-1,0
       0      .1       0   225.1    .045       0  238.88      .1       0
Bank Sta=225.1,238.88
XS Rating Curve= 0 ,0
Exp/Cntr(USF)=0,0
Exp/Cntr=0.3,0.1

Type RM Length L Ch R = 1 ,8500    ,502.3,505.8,502.1
XS GIS Cut Line= 6
1625337.95522884 441601.463551671625433.19421159441601.830020756
1625521.41975692441597.9409209191625595.82118292441588.381556839
1625695.22846442441577.5078909251625949.95925418441549.645741925
#Sta/Elev= 30
       0 1154.24    14.2 1141.12    30.2 1132.63    54.2  1111.2    74.2 1106.32
    90.2 1094.95   106.2 1080.96   117.9  1074.8   138.2 1067.81   166.2 1047.95
   186.3 1045.49   198.4 1039.34   230.6 1033.39   254.8 1024.66   287.7 1025.96
  304.62 1022.97   311.2 1022.59   317.8 1022.95   327.3 1025.99   375.6 1026.24
   387.6 1028.45   411.8 1037.91     440 1057.86   460.1 1069.65   484.2 1091.54
   504.3 1099.74   536.5 1108.44   564.7 1126.14   588.8 1134.67614.8141 1155.22
#Mann= 3 ,-1,0
       0      .1       0  304.62    .045       0   317.8      .1       0
Bank Sta=304.62,317.8
XS Rating Curve= 0 ,0
Exp/Cntr(USF)=0,0
Exp/Cntr=0.3,0.1

Type RM Length L Ch R = 1 ,7994    ,496.4,494.2,486.7
XS GIS Cut Line= 6
 1625286.8657641441940.9064423441625542.85278492441949.286018759
1625650.00447351 441965.26105243 1625738.1463576442000.009342507
 1625836.2308071442034.3478565071625944.81523558442052.851756498
#Sta/Elev= 30
       0 1107.41    25.3  1103.2    41.3 1098.87    62.9 1097.38    81.3  1092.9
    97.3  1087.3   125.3 1074.67   169.3 1060.81   185.3 1051.68   225.6 1032.31
   277.6 1027.44   285.7 1025.32   293.8  1019.5  296.93 1018.56     314 1017.89
   323.4 1018.56   334.2 1020.94   380.9 1023.57   478.2  1023.6   512.1 1027.08
   546.1 1038.88     563 1048.91   571.1 1055.99   579.2 1061.02   603.1  1070.1
   616.9 1081.77   627.9 1088.62   652.3 1099.27   664.4  1101.4673.2755 1105.66
#Mann= 3 ,-1,0
       0      .1       0  296.93    .045       0   323.4      .1       0
Bank Sta=296.93,323.4
XS Rating Curve= 0 ,0
Exp/Cntr(USF)=0,0
Exp/Cntr=0.3,0.1

Type RM Length L Ch R = 1 ,7500    ,499.5,500,500.9
XS GIS Cut Line= 6
1625446.51341067442444.9808935081625539.68251568442430.281775922
1625626.99139617442424.5029160831625701.82753259442419.547217339
  1625963.753846442402.200467259 1626057.2989345442396.004941583
#Sta/Elev= 30
       0 1136.86     9.7 1131.57    21.9 1129.73    58.3 1105.85    78.6 1100.85
    90.7 1093.17   106.8 1079.27   118.8 1072.05   138.9 1067.57   158.9 1059.28
     187 1040.21     211 1028.83     227 1018.76   239.1 1016.65   279.2 1016.33
   299.2 1012.15   307.2 1011.66  311.61 1012.13   335.3 1026.39   351.3 1027.91
   371.4 1037.16   411.4 1061.28   431.5 1066.77   447.5 1073.59   467.6 1084.56
   483.6 1095.85   495.6 1101.64   515.7 1107.27   599.9 1154.01613.0716 1159.86
#Mann= 3 ,-1,0
       0      .1       0   299.2    .045       0  311.61      .1       0
Bank Sta=299.2,311.61
XS Rating Curve= 0 ,0
Exp/Cntr(USF)=0,0
Exp/Cntr=0.3,0.1

Type RM Length L Ch R = 1 ,7000    ,498.3,504.3,511.1
XS GIS Cut Line= 6
1625510.50015934442869.3363440041625607.39202592442889.921932757
1625695.74913268442907.0160586681625771.09543867442911.892689332
1625945.86838309442902.9760405121626126.88278484442893.743119344
#Sta/Elev= 30
       0 1141.77    27.7 1130.21    58.9 1113.64    95.7 1101.52   120.2 1087.93
   132.4 1083.55   156.5 1070.79   169.1 1069.59   194.6 1060.39   209.5 1052.72
   217.5 1047.47   237.5 1028.31   249.5 1022.56   265.6 1012.87   273.6 1011.65
   285.6 1012.05   304.3 1008.58   317.6 1008.12  326.82 1008.57   337.3 1012.78
   357.7 1015.33   369.7 1019.92   381.7    1027   397.7 1029.38   409.7 1034.46
   461.8 1040.27   512.6 1044.37     558 1052.49     578  1058.4 620.804  1064.1
#Mann= 3 ,-1,0
       0      .1       0   304.3    .045       0  326.82      .1       0
Bank Sta=304.3,326.82
XS Rating Curve= 0 ,0
Exp/Cntr(USF)=0,0
Exp/Cntr=0.3,0.1

Type RM Length L Ch R = 1 ,6496    ,495.5,495.7,494.2
XS GIS Cut Line= 6
1625223.97612609443153.2760648431625460.35196568443252.223373502
1625550.37311108443299.2429645061625622.73779576443342.420043498
1625704.09491651443394.0183655021625786.39002751443453.307945088
#Sta/Elev= 30
       0 1122.94     8.8 1121.68    34.8 1128.03    43.5 1129.03    56.5 1128.61
    73.9 1126.07   101.7 1117.62   147.6 1105.78   156.3 1101.09   167.7 1092.75
   181.2 1077.35   189.1  1069.8     217 1052.18     243 1028.18   247.3 1025.65
   278.5  1013.8   287.6 1007.56   294.8 1004.02   305.6 1003.22  314.61 1004.02
   328.2 1007.06   337.2 1006.29   359.8 1010.27   405.3 1012.54   467.4 1020.12
   522.9 1034.32   576.9 1055.76   597.5 1060.18   632.1 1069.32639.8464 1070.32
#Mann= 3 ,-1,0
       0      .1       0   294.8    .045       0  314.61      .1       0
Bank Sta=294.8,314.61
XS Rating Curve= 0 ,0
Exp/Cntr(USF)=0,0
Exp/Cntr=0.3,0.1

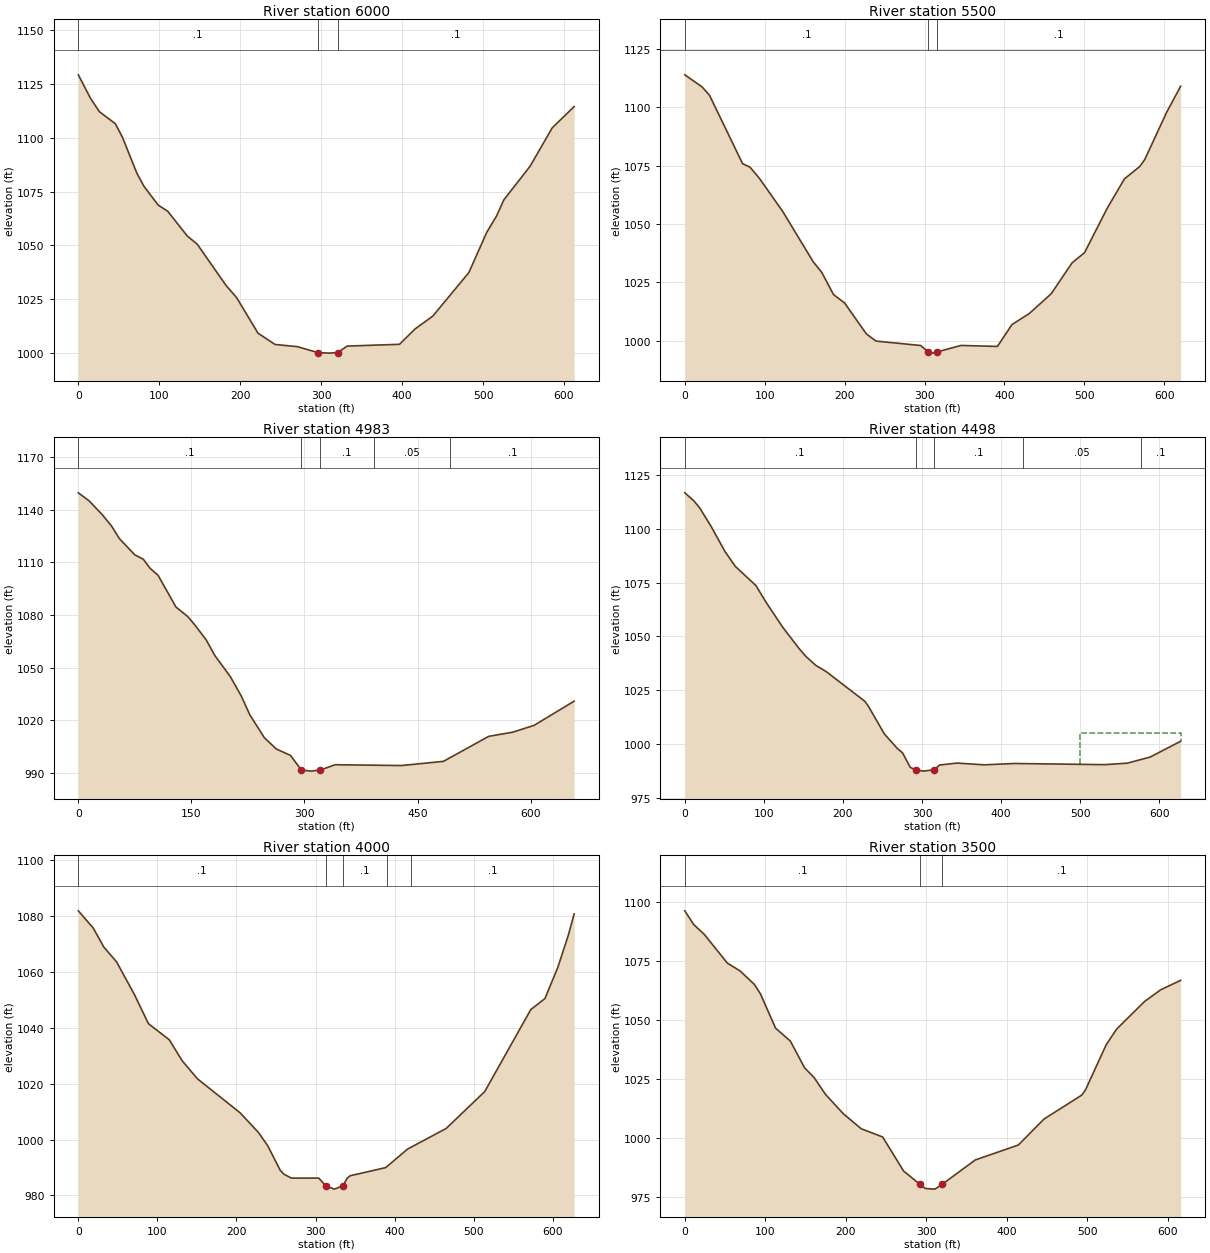
Type RM Length L Ch R = 1 ,6000    ,497.4,500,504.8
XS GIS Cut Line= 6
1625006.52478933443579.5731125031625091.64601018443618.859451249
1625239.18935026443686.9567560111625398.08207709443760.291583091
1625476.74924259443798.6484617591625560.07125442443841.833086669
#Sta/Elev= 30
       0 1129.27      15 1118.38      26 1112.14    45.8 1106.52    54.6 1100.16
    72.2 1083.64      81 1077.48    98.7 1068.68   110.4 1065.86   134.6 1054.35
   147.1 1050.44   182.4 1031.41   195.6 1025.67     222 1009.15   243.1 1003.89
   270.5 1002.89   295.8 1000.14   310.1  999.87   320.4 1000.12   332.2 1003.15
   396.8 1003.97   415.9 1011.07     438  1017.1   482.5 1037.32   504.7 1056.09
   516.7 1063.59   525.6 1071.06   558.3 1086.84   585.6 1104.66612.6179 1114.51
#Mann= 3 ,-1,0
       0      .1       0   295.8    .045       0   320.4      .1       0
Bank Sta=295.8,320.4
XS Rating Curve= 0 ,0
Exp/Cntr(USF)=0,0
Exp/Cntr=0.3,0.1

Type RM Length L Ch R = 1 ,5500    ,513.7,516.8,514.1
XS GIS Cut Line= 6
1624893.67002818443797.7705107631624940.30740209443879.128615752
1625065.33110218444109.9427866791625101.44126618444175.679531842
1625159.73872176444245.0524245951625226.97907284444317.124130845
#Sta/Elev= 30
       0 1113.91    21.4 1108.81    30.9 1105.17    72.3 1075.84    81.6 1074.34
    93.4 1069.54   122.7 1055.28   160.6 1033.85   171.4 1029.24   186.1 1019.75
     200 1016.12   227.3 1002.85   239.3  999.81   295.3  997.91   304.6  995.19
   310.1  994.65  315.72  995.17   345.6  997.94   391.2  997.52   409.4 1006.88
   431.3 1011.67   458.5  1020.1   484.6 1033.32   500.3 1037.74   528.3 1056.55
   550.1  1069.3   569.4 1074.65   575.6 1077.63   603.2 1098.01620.4622    1109
#Mann= 3 ,-1,0
       0      .1       0   304.6    .045       0  315.72      .1       0
Bank Sta=304.6,315.72
XS Rating Curve= 0 ,0
Exp/Cntr(USF)=0,0
Exp/Cntr=0.3,0.1

Type RM Length L Ch R = 1 ,4983    ,500.5,485.1,475.7
XS GIS Cut Line= 6
 1624568.7428565443964.0838264231624712.41087626444176.271066085
 1624740.6995336444278.2626600121624740.03549293444369.870744511
1624744.63784592444470.8137840931624752.17227967444573.590809509
#Sta/Elev= 30
       0 1149.57    14.3    1145    31.6  1137.2      44 1130.72    54.6 1123.43
    74.8  1114.3    86.3 1111.72    94.9 1106.72   105.9 1102.54   129.5 1084.57
   145.5 1078.99   155.4 1073.88   169.6 1065.87   181.2 1056.85   201.5 1045.01
   215.9 1034.09   227.6  1023.1   246.9 1010.08   262.7 1003.69   281.4 1000.08
  295.82  991.78   308.2   991.1   321.2  991.75   340.7  994.75   428.5  994.28
   484.4  996.66   544.4  1010.9   576.5 1013.29   604.6 1017.15 657.803 1030.93
#Mann= 5 ,-1,0
       0      .1       0  295.82    .045       0   321.2      .1       0
  392.09     .05       0   493.7      .1       0
Bank Sta=295.82,321.2
XS Rating Curve= 0 ,0
Exp/Cntr(USF)=0,0
Exp/Cntr=0.3,0.1

Type RM Length L Ch R = 1 ,4498    ,492.8,497.9,503.7
XS GIS Cut Line= 6
1624037.43256742 444385.192236171624208.24128093444449.864679009
1624378.45846017444490.6772614271624448.21914743444522.474441916
1624525.60613176444572.1147625891624602.07481085444637.517518923
#Sta/Elev= 30
       0 1116.82    11.6 1113.07    18.6 1109.93    33.4 1101.14    50.8 1089.53
    63.9 1082.62      90 1073.68   102.8  1065.9   123.8 1054.33   144.8 1044.28
   153.2 1040.72   165.9 1036.52   178.5 1033.76   227.7 1019.88   232.1 1017.63
   252.3 1004.74   268.7  997.97   275.4  995.89   285.2  989.13   291.8     988
   301.8  987.38  315.35  988.02   322.4  990.23   344.4  991.12   378.7  990.31
   416.9  990.93   531.4  990.39   559.8  991.09   588.7  993.94627.1294 1001.26
#Mann= 5 ,-1,0
       0      .1       0   291.8    .045       0  315.35      .1       0
   427.9     .05       0  576.51      .1       0
#XS Ineff= 2 , 0
                          500.33         1005.22
Permanent Ineff=
       F       F
Bank Sta=291.8,315.35
XS Rating Curve= 0 ,0
Exp/Cntr(USF)=0,0
Exp/Cntr=0.3,0.1

Type RM Length L Ch R = 1 ,4000    ,495.1,500.2,504.9
XS GIS Cut Line= 6
1623914.31207876444777.7741281691624007.42016026 444816.88723892
1624090.49086025444856.8005449181624157.17314158444896.500596762
1624230.58834909444964.4007234281624419.48429675445137.554576591
#Sta/Elev= 30
       0 1081.86    18.8 1075.72    32.3 1068.86    48.4 1063.57    70.7 1052.02
    88.7 1041.46   115.1 1035.69   131.2 1028.24   150.6 1021.75   204.4 1009.61
   227.6  1002.6   239.6  997.74   255.4  988.93   260.2  987.56   269.5   986.2
     304   986.2  312.78  983.48   323.8  982.25   334.7  983.45   340.1  986.21
   343.6  987.03   388.7  989.95   416.2  996.56   465.1 1003.95   513.9 1017.16
   572.2 1046.53     590 1050.44   606.2 1061.49   619.6 1073.11627.0081 1080.75
#Mann= 5 ,-1,0
       0      .1       0  312.78    .045       0   334.7      .1       0
  390.76     .05       0  420.76      .1       0
Bank Sta=312.78,334.7
XS Rating Curve= 0 ,0
Exp/Cntr(USF)=0,0
Exp/Cntr=0.3,0.1

Type RM Length L Ch R = 1 ,3500    ,499.7,503.3,504.3
XS GIS Cut Line= 6
1623687.72034034444962.5444279161623797.89203601445193.901904836
1623840.88538834445284.1881415841623873.98112267445351.497390166
1623920.09979685445426.9122655841623977.90184659445504.310076669
#Sta/Elev= 30
       0 1096.15    11.1 1090.35    24.4 1086.13    52.8 1074.07    68.7 1070.71
    86.4 1065.05      94 1061.03   112.8 1046.51   131.2 1041.04   148.8 1029.78
   160.9  1025.5     175 1018.43   197.1 1010.26   219.3 1003.93   245.9 1000.46
   271.9  986.07   292.1  980.45   298.9  978.66   310.9  978.39   319.9  980.45
   361.1  990.75   414.6  997.06   446.5 1008.06   493.4 1018.18   498.1 1020.45
   523.7 1039.44   536.7  1046.1   571.6 1057.84   591.6 1062.76616.2544 1066.73
#Mann= 3 ,-1,0
       0      .1       0   292.1    .045       0   319.9      .1       0
Bank Sta=292.1,319.9
XS Rating Curve= 0 ,0
Exp/Cntr(USF)=0,0
Exp/Cntr=0.3,0.1