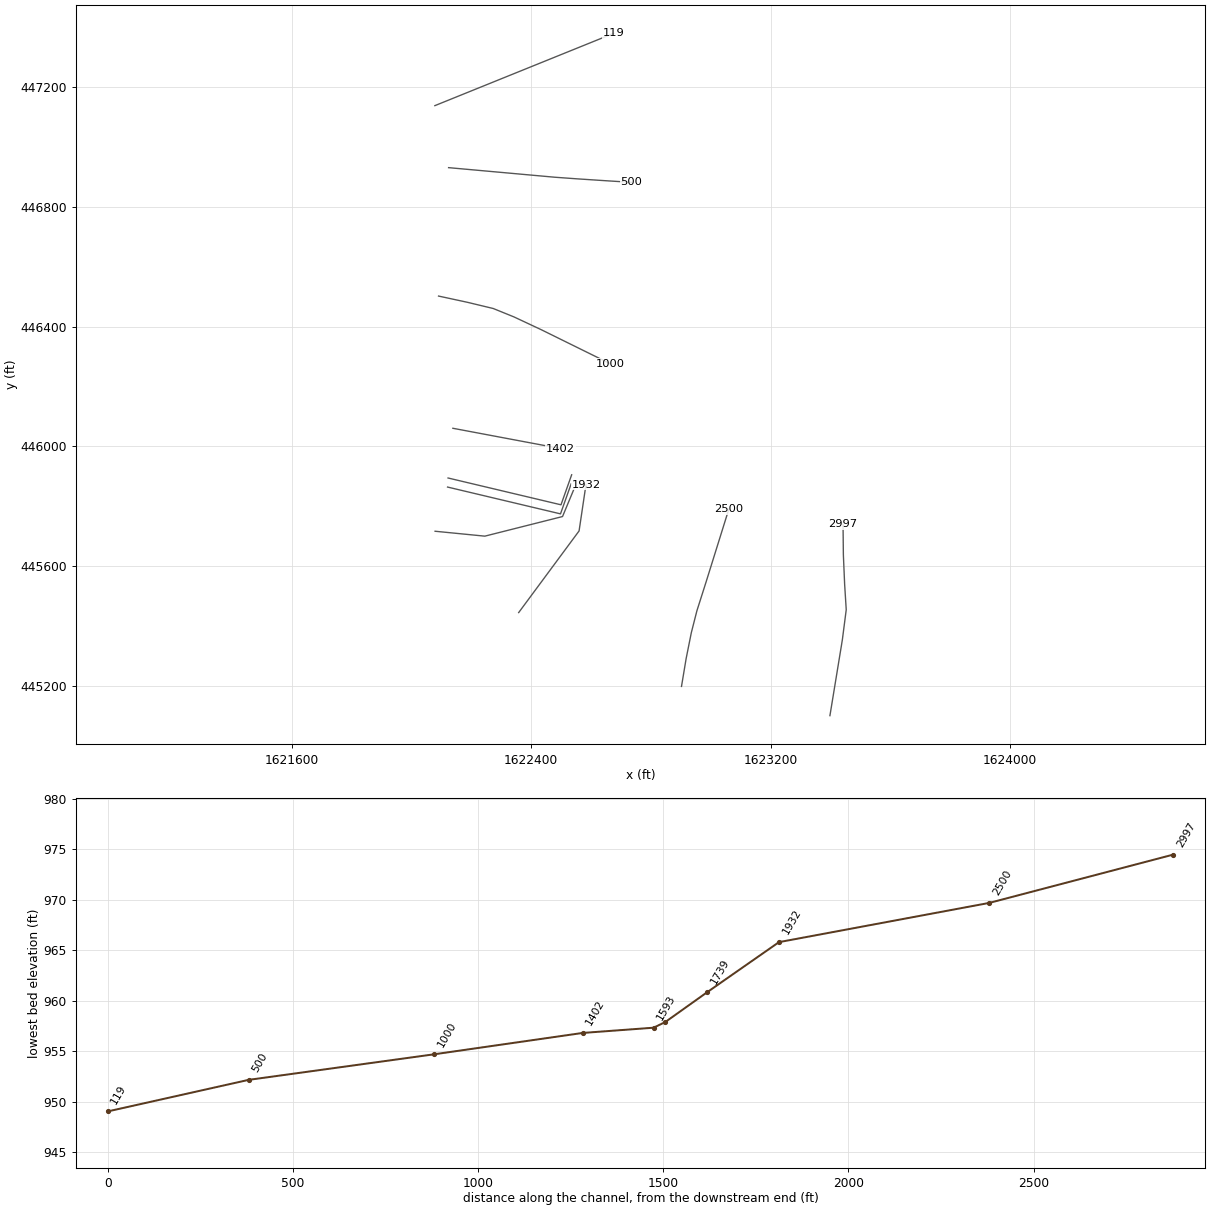
HEC-RAS study WHTSTNECK.prj: WHTSTNECK

--- WHTSTNECK.g01 (geometry) --- (continued)

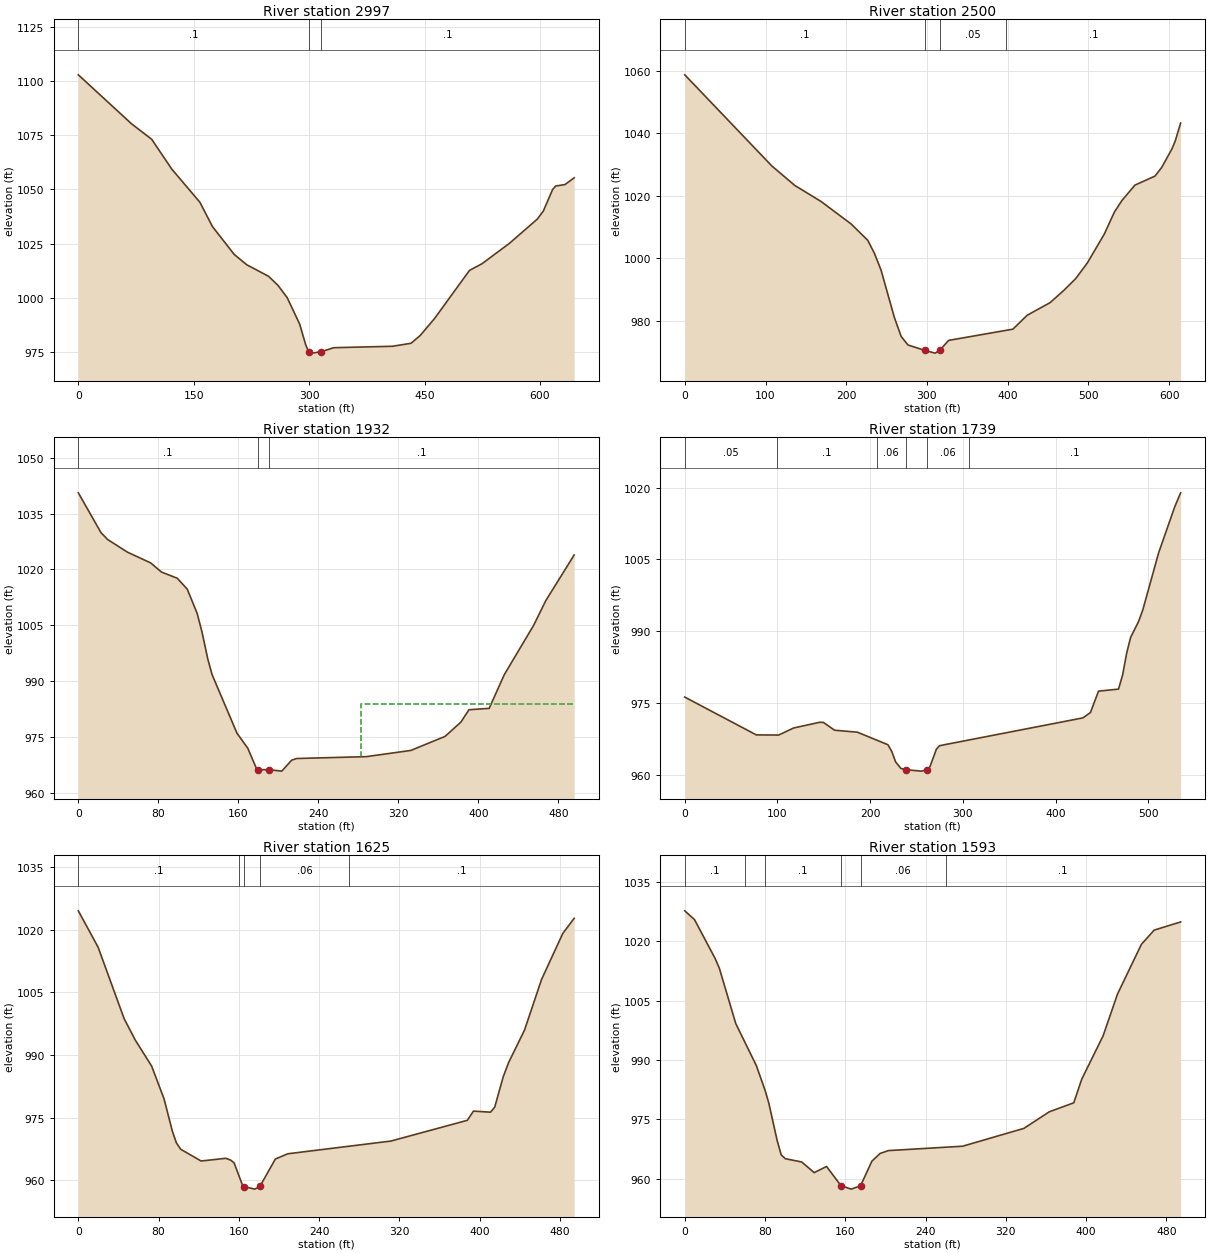
Type RM Length L Ch R = 1 ,2997    ,498.4,497,495.2
XS GIS Cut Line= 6
1623398.45812359445100.5950048421623439.88947117445353.409787923
1623452.93865767445454.4463312631623447.60599117445539.696160749
1623443.38224635445637.7770013361623442.26118559445740.534341753
#Sta/Elev= 30
       0 1102.75    68.8 1080.29    95.4 1073.02   121.5 1059.28     158 1044.02
   174.2 1032.89   202.6 1019.97   218.8 1015.24   247.2 1009.91   259.3  1005.8
   271.4 1000.09   287.6  987.93   295.6  978.25  299.29  975.16   303.7  974.49
   315.8  975.16   331.9  976.99   408.3  977.65   432.3  979.02   444.3  982.61
     463  990.45   508.4 1012.62   524.4 1015.63   560.4 1025.12   596.4 1036.22
   604.4    1040   616.4 1049.89   620.4 1051.51   632.4 1052.17644.4146 1055.27
#Mann= 3 ,-1,0
       0      .1       0  299.29    .045       0   315.8      .1       0
Bank Sta=299.29,315.8
XS Rating Curve= 0 ,0
Exp/Cntr(USF)=0,0
Exp/Cntr=0.3,0.1

Type RM Length L Ch R = 1 ,2500    ,567.2,568,566.8
XS GIS Cut Line= 6
1622902.56508651 445198.289363251622918.09228642 445291.46076484
  1622935.417383445377.928111583 1622954.0357841445451.009986416
1622984.40055275 445546.310320751623060.78393017445790.835750341
#Sta/Elev= 30
       0 1058.73   107.8 1029.58   136.3 1023.34     169 1018.18     206 1011.03
   226.6 1005.82   234.9 1001.64   243.1  996.29   259.7  981.06   268.1  975.02
   276.5  972.31   297.4  970.57     310   969.7  315.74  970.56   326.8  973.77
   406.5  977.37   424.2  981.82   452.6  985.86   469.4  989.74   484.2  993.51
   498.7  998.55   519.7 1007.78   532.2 1014.82   541.6 1018.55   557.6 1023.44
   582.5 1026.33   590.9 1029.14   603.5 1035.03   607.7 1037.65614.2573 1043.31
#Mann= 4 ,-1,0
       0      .1       0   297.4    .045       0  315.74     .05       0
  398.08      .1       0
Bank Sta=297.4,315.74
XS Rating Curve= 0 ,0
Exp/Cntr(USF)=0,0
Exp/Cntr=0.3,0.1

Type RM Length L Ch R = 1 ,1932    ,201.5,193,186.3
XS GIS Cut Line= 3
1622358.61837905445445.0249788731622560.40564078445717.760273271
1622583.44071632445872.555980902
#Sta/Elev= 30
       0 1040.56    22.7 1029.85    29.3 1028.02    49.2 1024.61    72.2 1021.76
    83.2 1019.27    98.9 1017.62   108.9 1014.69   118.8 1008.19   123.7 1003.12
   129.4  995.98   133.7  991.76   158.6  976.01   169.5  971.94     178  966.57
  179.57   966.2  190.21   966.2   203.4  965.81   213.4  968.77   218.3   969.2
     288   969.7   332.5  971.37   366.7  975.14   382.5  978.97   390.6   982.3
   410.8  982.67   425.9  991.72   455.3 1004.99   467.4  1011.6 495.768 1023.86
#Mann= 3 ,-1,0
       0      .1       0  179.57    .045       0  190.21      .1       0
#XS Ineff= 2 , 0
                          282.49          983.82
Permanent Ineff=
       F       F
Bank Sta=179.57,190.21
XS Rating Curve= 0 ,0
Exp/Cntr(USF)=0,0
Exp/Cntr=0.3,0.1

Type RM Length L Ch R = 1 ,1739    ,115.3,114,108.9
XS GIS Cut Line= 4
1622079.27701172445716.7166030061622245.51994068445700.337989315
1622505.12096767445765.8524440771622543.61070984445858.391611429
#Sta/Elev= 30
       0   976.3    77.2  968.42   101.3  968.39   117.4  969.86   145.5  971.05
   149.6  971.02   161.6   969.4   186.2  968.99   219.2  966.37   223.4  964.94
   227.5  962.78   233.2  961.43   238.5  961.17     255  960.87   261.6  961.12
   264.6  961.84   271.5  965.46   274.8  966.17   429.6  971.97   437.7  973.09
   446.4  977.54     468  977.97   472.4  980.91   476.7  985.38     481  988.73
   489.7  992.09   494.2  994.49   511.3  1006.4   528.7    1016     535 1018.89
#Mann= 6 ,-1,0
       0     .05       0     100      .1       0  207.05     .06       0
   238.5    .045       0   261.6     .06       0  307.05      .1       0
Bank Sta=238.5,261.6
XS Rating Curve= 0 ,0
Exp/Cntr(USF)=0,0
Exp/Cntr=0.3,0.1

Type RM Length L Ch R = 1 ,1625    ,33.3,31.5,31.9
XS GIS Cut Line= 3
1622120.98853977 445864.355494011622498.30307712445774.795120309
1622533.96137406445875.135909363
#Sta/Elev= 30
       0  1024.5    19.7  1015.8    45.6  998.72    56.7  993.59    73.1  987.33
    85.4  979.54    93.7   971.8    97.8  968.93   102.1  967.43   122.4  964.62
   147.1  965.27     152  964.82   155.3  964.17   163.5  958.93   165.2   958.5
   175.9  957.89     181  958.53   196.4  965.09   208.8  966.35   311.5  969.39
   387.8  974.36   393.9  976.56   410.9  976.31   415.1  977.51   423.6   984.8
     429  988.21   444.8  995.95   461.8 1008.08     483 1019.11494.2865  1022.7
#Mann= 5 ,-1,0
       0      .1       0     160     .06       0   165.2    .045       0
     181     .06       0     270      .1       0
Bank Sta=165.2,181
XS Rating Curve= 0 ,0
Exp/Cntr(USF)=0,0
Exp/Cntr=0.3,0.1

Type RM Length L Ch R = 1 ,1593    ,193.4,191.5,189.8
XS GIS Cut Line= 3
1622122.64706521 445894.623583271622499.96160256445805.063209569
 1622535.6198995445905.403998623
#Sta/Elev= 30
       0 1027.68     9.7 1025.45    30.3 1015.61    34.4 1013.21    50.8  999.19
    71.4  988.51      80  982.33    83.7  979.14      92   969.7    96.1  965.99
   100.2  965.02   116.6  964.19     129   961.5   141.3  963.06   155.8  958.17
     166  957.33  175.23  958.18   186.5  964.39   194.7  966.35     203  967.07
     277  968.18   338.1  972.69   363.3  976.87   387.8  979.16   395.7  985.12
     417  996.07   431.4 1006.66   455.2 1019.21   467.9  1022.8494.2865 1024.87
#Mann= 6 ,-1,0
       0      .1       0      60     .06       0      80      .1       0
   155.8    .045       0  175.23     .06       0     260      .1       0
Bank Sta=155.8,175.23
XS Rating Curve= 0 ,0
Exp/Cntr(USF)=0,0
Exp/Cntr=0.3,0.1

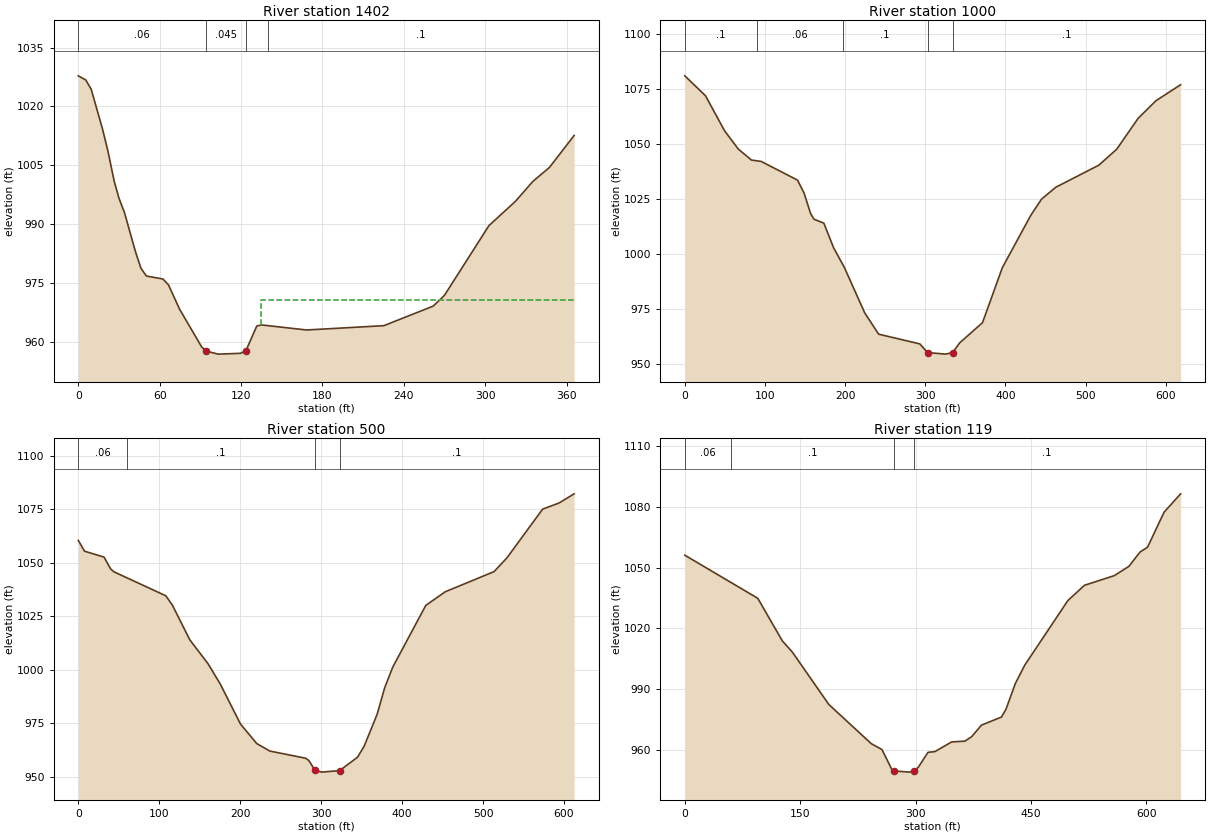
Type RM Length L Ch R = 1 ,1402    ,405.4,401.8,397.8
XS GIS Cut Line= 2
1622138.74090465446060.7269535391622498.08808308445993.157398621
#Sta/Elev= 30
       0 1027.82     5.5 1026.76     9.5 1024.38    17.7 1014.42    21.7 1008.81
    26.5 1000.86    29.9  996.65      34  992.96    42.1     983    46.2   978.7
    50.2  976.74    62.4  975.98    66.5  974.47    74.7  968.26    90.9  958.68
   93.88  957.61   103.1  956.81   119.4  957.01   123.5  957.61   131.6  963.98
   134.9  964.27   168.3  962.97   225.3  964.07   261.7  969.06     270  971.81
   302.8   989.6   322.3  995.78   335.1 1000.85   347.4 1004.44365.6447 1012.61
#Mann= 4 ,-1,0
       0     .06       0   93.88    .045       0   123.5     .06       0
     140      .1       0
#XS Ineff= 2 , 0
                           134.8          970.59
Permanent Ineff=
       F       F
Bank Sta=93.88,123.5
XS Rating Curve= 0 ,0
Exp/Cntr(USF)=0,0
Exp/Cntr=0.3,0.1

Type RM Length L Ch R = 1 ,1000    ,496.3,500,506.9
XS GIS Cut Line= 6
1622090.91874392 446502.461295591622186.11704434446481.898344591
1622273.52697451446460.9075729251622343.12755708446432.682563752
1622433.67330776446390.2390790881622663.54916035446276.895473748
#Sta/Elev= 30
       0 1080.86    25.8 1071.85    49.7 1055.91    66.7 1047.68    83.1 1042.69
    95.3 1042.05   140.6 1033.59   148.8 1027.75     157 1018.41   161.2 1015.85
   173.5 1014.08   185.8 1002.82   198.9  994.14   224.6  973.33   241.9  963.74
   293.3  959.32  302.91   955.4   325.3  954.69   334.2   955.4     343  959.79
   371.5  968.97   396.2  993.86   431.8 1017.66   445.2 1024.98     463 1030.36
   516.6 1040.35   538.9 1047.56   565.7  1061.6     588 1069.59618.6969 1076.83
#Mann= 5 ,-1,0
       0      .1       0      90     .06       0  197.29      .1       0
  302.91    .045       0   334.2      .1       0
Bank Sta=302.91,334.2
XS Rating Curve= 0 ,0
Exp/Cntr(USF)=0,0
Exp/Cntr=0.3,0.1

Type RM Length L Ch R = 1 ,500     ,373.1,380.7,386.9
XS GIS Cut Line= 6
1622124.47970042446931.4742170871622217.85090476446923.056254923
1622479.29034251446899.483139336 1622554.1074501446894.082231507
1622641.44323343446888.3227285891622735.03786251446882.384420261
#Sta/Elev= 30
       0 1060.34     7.7 1055.32    31.8 1052.56    39.8 1047.12    43.8 1045.73
   108.1  1034.5   116.1 1030.22   137.6 1014.01   160.3 1002.75   175.5  993.19
   200.4  974.58   220.5  965.48   236.6     962   280.8  958.65   284.8  957.58
  292.49  952.94   300.9  952.16   322.9  952.89     345  959.15   353.1  964.26
   369.1  979.09   378.5  991.59   388.5 1001.23   429.3 1030.03   453.4 1036.39
   513.6 1045.79   529.5 1052.19   573.6 1074.96   593.6 1077.77612.5701 1082.11
#Mann= 4 ,-1,0
       0     .06       0      60      .1       0  292.49    .045       0
   322.9      .1       0
Bank Sta=292.49,322.9
XS Rating Curve= 0 ,0
Exp/Cntr(USF)=0,0
Exp/Cntr=0.3,0.1

Type RM Length L Ch R = 1 ,119     ,,,
XS GIS Cut Line= 2
1622078.52412559447138.6129025061622676.04021763447380.248005717
#Sta/Elev= 30
       0 1056.23    94.9 1034.91   126.8 1013.87   139.8 1008.34   187.2  982.48
   242.3  963.12   256.3  960.19   269.2  950.29   271.9  949.64   291.5  949.03
   297.6  949.35   303.7  951.52   316.1  958.79   325.2  959.18   346.9  963.96
   364.1  964.33   372.8  966.52   385.7  972.27   411.6  976.23   417.5  980.09
   429.7  992.83   441.8 1001.82   497.9 1033.77   519.5 1041.34   558.3 1046.12
   577.2 1050.68   591.9 1057.83   601.5 1060.13     623 1077.46644.5254 1086.54
#Mann= 4 ,-1,0
       0     .06       0      60      .1       0   271.9    .045       0
   297.6      .1       0
Bank Sta=271.9,297.6
XS Rating Curve= 0 ,0
Exp/Cntr(USF)=0,0
Exp/Cntr=0.3,0.1
LCMann Table=0

Chan Stop Cuts=-1
Use User Specified Reach Order=0
Composite Channel Slope=5